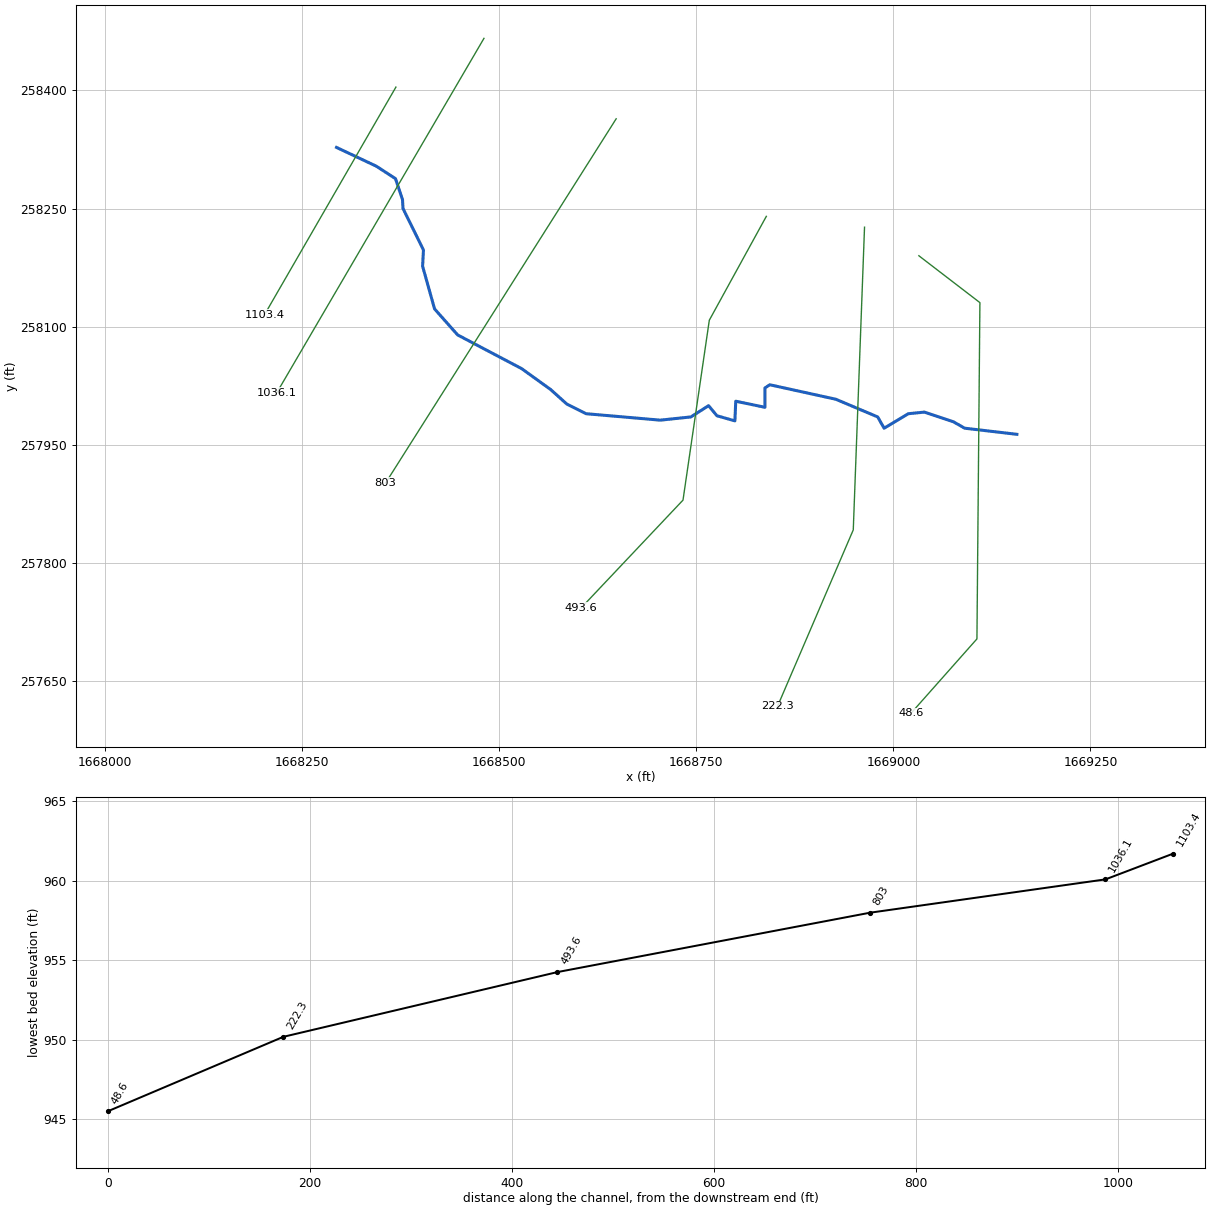
--- LIISAACCK.prj (project) ---

Proj Title=LIISAACCK
Current Plan=p01
Default Exp/Contr=0,0
English Units
Geom File=g01
Flow File=f01
Plan File=p01
BEGIN DESCRIPTION:
END DESCRIPTION:
DSS Export Rating Curves= 0
DSS Export Rating Curve Sorted= 0
DSS Export Volume Flow Curves= 0
DXF OffsetX= 0
DXF OffsetY= 0
DXF ScaleX= 0
DXF ScaleY= 0

--- LIISAACCK.p01 (plan) ---

Plan Title=Floodplain
Program Version=4.00
Geom File=g01
Flow File=f01
K Sum by GR=0
Std Step Tol=0.01
Critical Tol=0.01
Num of Std Step Trials=20
Max Error Tol=0.3
Flow Tol Ratio=0.001
Split Flow NTrial=30
Split Flow Tol=0.02
Split Flow Ratio=0.02
Log Output Level=0
Friction Slope Method=1
Unsteady Friction Slope Method=2
Unsteady Bridges Friction Slope Method=1
Global Log Level=0
CheckData=False
Run HTab=0
Run UNet=0
Run PostProcess=0
UNET Theta=0
UNET Theta Warmup=0
UNET ZTol=0
UNET ZSATol=0
UNET MxIter=0
UNET MaxInSteps=0
UNET DtIC=0
UNET DtMin=0
UNET MaxCRTS=0
UNET WFStab=0
UNET SFStab=0
UNET WFX=0
UNET SFX=0
UNET DSS MLevel=0
UNET DZMax Abort=0
UNET Convert EG Bridges=0
UNET Use Existing IB Tables=0
UNET Froude Limit=0
UNET Froude Power=0
Write IC File=0
Echo Input=False
Echo Output=False
Write Detailed=0

--- LIISAACCK.f01 (steady flow) ---

Flow Title=NFF Regression Equation
Program Version=4.10
Number of Profiles= 1
Profile Names=P100yr
River Rch & RM=LIISAACCK,Main            ,1103.4
333.2484
River Rch & RM=LIISAACCK,Main            ,493.6
342.3865
River Rch & RM=LIISAACCK,Main            ,222.3
347.1575
Boundary for River Rch & Prof#=LIISAACCK,Main            , 1
Up Type= 0
Dn Type= 3
Dn Slope=0.02786
DSS Import GetInterval= 0
DSS Import GetPeak= 0
DSS Import FillOption= 0

--- LIISAACCK.g01 (geometry) ---

Geom Title=USGS 10m DEM
Program Version=4.10

River Reach=LIISAACCK       ,Main
Reach XY= 30
     1668293.868      258327.706     1668344.433      258303.834
     1668368.652      258288.039     1668377.581      258261.251
      1668378.13       258250.27     1668404.111      258197.497
     1668403.026      258176.881     1668418.217      258122.628
     1668447.429      258089.646      1668528.74       258046.77
     1668565.508      258020.215     1668585.935      258001.831
     1668610.447      257989.575      1668704.41      257981.404
     1668743.221      257985.489     1668765.691      257999.788
      1668776.29      257986.994     1668799.077      257980.483
     1668800.162       258005.44     1668837.185      257997.745
     1668837.185      258022.258     1668843.312      258026.343
     1668927.063      258007.959     1668980.172      257985.489
     1668988.343      257971.191     1669018.983      257989.575
      1669039.41      257991.618     1669076.178      257979.361
     1669090.477      257971.191      1669156.66      257963.428

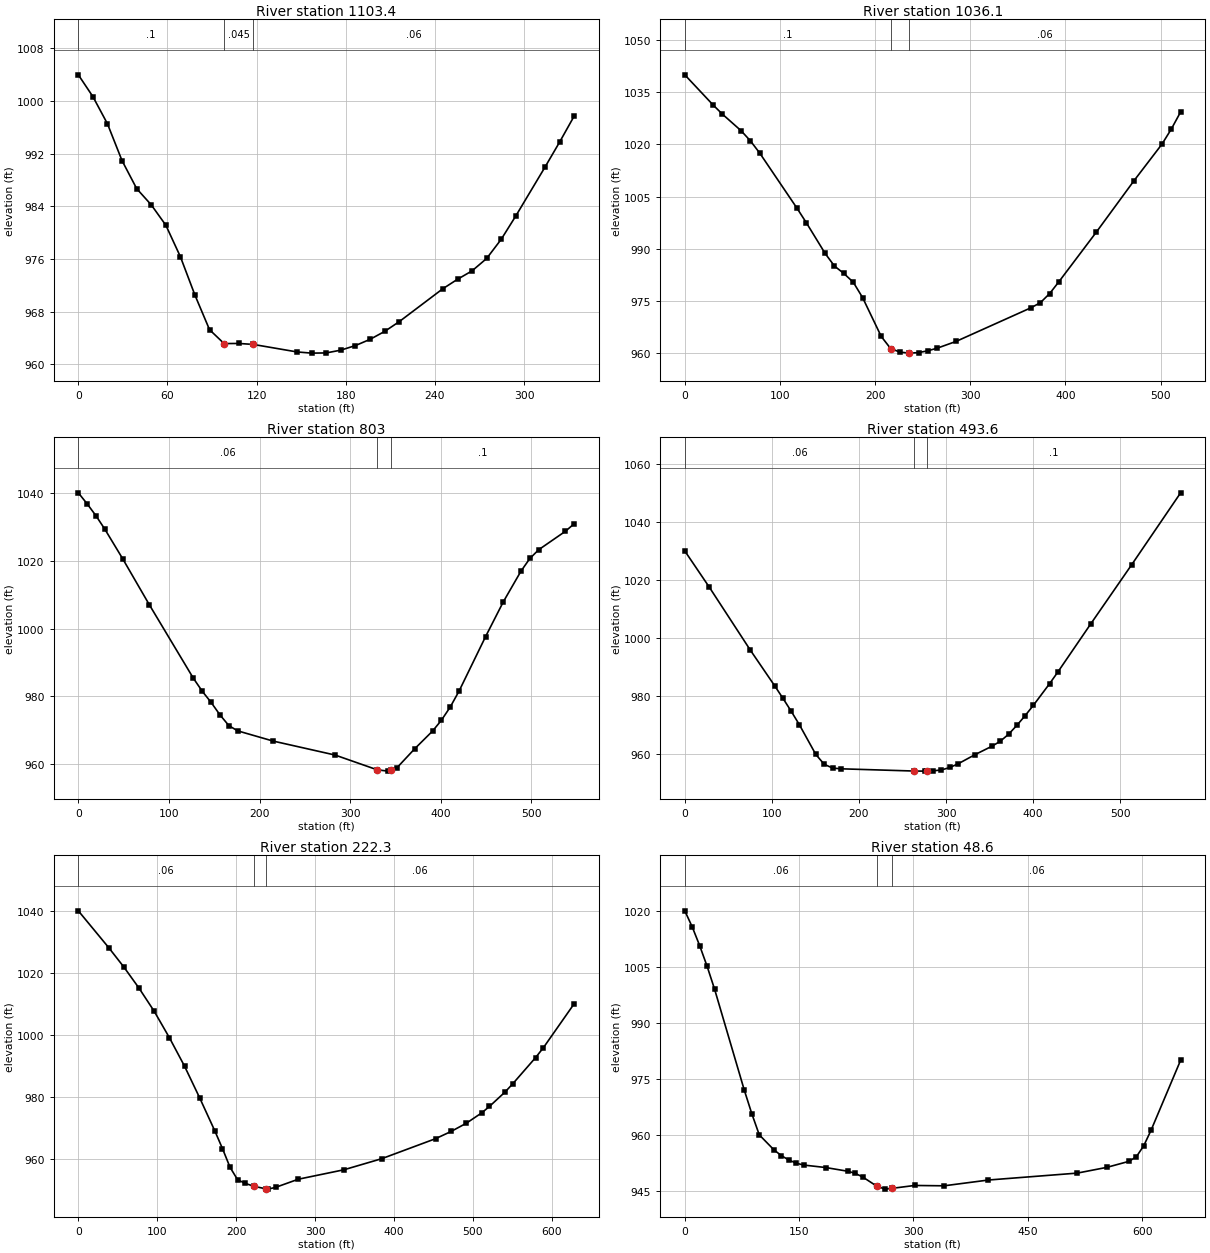
Type RM Length L Ch R = 1 ,1103.4  ,64.9,67.3,71.5
XS GIS Cut Line= 2
     1668369.172      258404.312     1668202.505      258115.249
#Sta/Elev= 30
       0    1004     9.8 1000.69    19.6  996.56    29.4  990.97    39.3   986.7
    49.1  984.24    58.9  981.15    68.7  976.36    78.5  970.52    88.3  965.28
    98.1  963.17     108  963.19   117.8  963.04   147.2   961.9     157  961.72
   166.8  961.75   176.6  962.17   186.5  962.87   196.3  963.81   206.1  965.01
   215.9  966.49   245.3   971.5   255.2  972.94     265  974.22   274.8   976.1
   284.6  979.01   294.4  982.55     314  989.95   323.9  993.78   333.7  997.73
#Mann= 3 , 0 , 0
       0      .1       0    98.1    .045       0   117.8     .06       0
Bank Sta=98.1,117.8
XS Rating Curve= 0 ,0
Exp/Cntr=0.3,0.1

Type RM Length L Ch R = 1 ,1036.1  ,236.4,233.1,227.2
XS GIS Cut Line= 2
     1668480.868      258466.245      1668218.13      258016.291
#Sta/Elev= 30
       0    1040    29.5 1031.41    39.3 1028.76      59 1023.99    68.8 1021.09
    78.6 1017.58     118 1001.66   127.8  997.49   147.5   988.7   157.3  985.08
   167.1  982.97     177  980.46   186.8  976.05   206.4  964.88   216.3   961.4
   226.1  960.38     236  960.09   245.8  960.24   255.6  960.78   265.4  961.53
   285.1  963.46   363.8  973.12   373.6  974.57   383.4   977.2   393.2  980.63
   432.6   994.9   471.9 1009.56   501.4  1020.1   511.2 1024.42     521 1029.35
#Mann= 3 , 0 , 0
       0      .1       0   216.3    .045       0     236     .06       0
Bank Sta=216.3,236
XS Rating Curve= 0 ,0
Exp/Cntr=0.3,0.1

Type RM Length L Ch R = 1 ,803     ,302.9,309.4,317.1
XS GIS Cut Line= 2
     1668648.529      258364.083     1668356.151      257901.707
#Sta/Elev= 30
       0    1040     9.8 1036.73    19.5 1033.23    29.3 1029.26    48.8 1020.64
    78.2 1007.08     127  985.33   136.8  981.51   146.5  978.25   156.3  974.56
   166.1   971.4   175.8  969.86   214.9  966.85   283.3  962.73     330  958.36
   341.9  957.99     345  958.32   351.7  959.02   371.2  964.59   390.8  969.78
   400.5  972.94   410.3  976.85   420.1  981.58   449.4  997.65   468.9 1007.87
   488.4 1016.91   498.2 1020.65     508 1023.24   537.3 1028.64   547.1 1030.88
#Mann= 3 , 0 , 0
       0     .06       0     330    .045       0     345      .1       0
Bank Sta=330,345
XS Rating Curve= 0 ,0
Exp/Cntr=0.3,0.1

Type RM Length L Ch R = 1 ,493.6   ,261.3,271.4,272.3
XS GIS Cut Line= 4
     1668838.942      258240.209     1668766.637        258108.3
     1668733.276      257879.875     1668604.194      257743.124
#Sta/Elev= 30
       0    1030    28.2 1017.51    75.2   995.9   103.4  983.52   112.8  979.25
   122.2  974.84   131.6  970.19   150.4     960     160  956.62   169.7   955.3
   179.3  955.05   263.2  954.28   275.5  954.25   278.2  954.28   285.1  954.35
   294.7  954.66   304.3   955.5   313.9  956.78   333.2  959.92   352.4  962.78
     362  964.48   371.7  966.92   381.3  970.01   390.7  973.31   400.1  976.84
   418.9  984.36   428.3  988.34   465.9 1004.82   512.9 1025.18   569.3    1050
#Mann= 3 , 0 , 0
       0     .06       0   263.2    .045       0   278.2      .1       0
Bank Sta=263.2,278.2
XS Rating Curve= 0 ,0
Exp/Cntr=0.3,0.1

Type RM Length L Ch R = 1 ,222.3   ,163.7,173.7,176.8
XS GIS Cut Line= 3
     1668963.485      258226.414     1668949.208      257842.078
     1668853.135      257618.054
#Sta/Elev= 30
       0    1040    38.5 1028.12    57.7 1021.86    76.9 1015.05    96.2 1007.56
   115.4  999.06   134.6  989.86   153.8  979.62   173.1   968.9   182.7  963.24
   192.3   957.2   201.9  953.19   211.5  952.03   222.3  951.11   237.3  950.28
   240.4  950.17     250  950.74   278.8  953.37   336.5  956.41   384.6     960
   452.8  966.46   472.4  968.78   491.8  971.45   511.4  974.81   521.1  976.88
   540.6  981.46   550.4  984.12   579.6  992.65   589.4  995.82   628.4    1010
#Mann= 3 , 0 , 0
       0     .06       0   222.3    .045       0   237.3     .06       0
Bank Sta=222.3,237.3
XS Rating Curve= 0 ,0
Exp/Cntr=0.3,0.1

Type RM Length L Ch R = 1 ,48.6    ,51,48.6,46.2
XS GIS Cut Line= 4
     1669032.382      258190.173     1669109.815      258130.637
     1669106.043      257703.642      1669022.54      257609.366
#Sta/Elev= 30
       0    1020     9.8 1015.67    19.5 1010.69    29.3 1005.13    39.1     999
    78.1  971.96    87.9  965.69    97.7  960.02   117.1  955.97   126.8  954.44
   136.5  953.27   146.2  952.43   155.9  951.93     185  951.26   214.1  950.26
   223.8  949.69   233.5  948.72   251.7   946.3   262.7  945.48   272.4   945.7
   301.5  946.46   340.3  946.37   398.5  947.92     515  949.77   553.8  951.31
   582.8  952.92   592.5  954.15   602.2  957.09   611.9  961.29   650.6     980
#Mann= 3 , 0 , 0
       0     .06       0   251.7    .045       0   272.4     .06       0
Bank Sta=251.7,272.4
XS Rating Curve= 0 ,0
Exp/Cntr=0.3,0.1

Chan Stop Cuts=-1
Use User Specified Reach Order=0
Composite Channel Slope=5